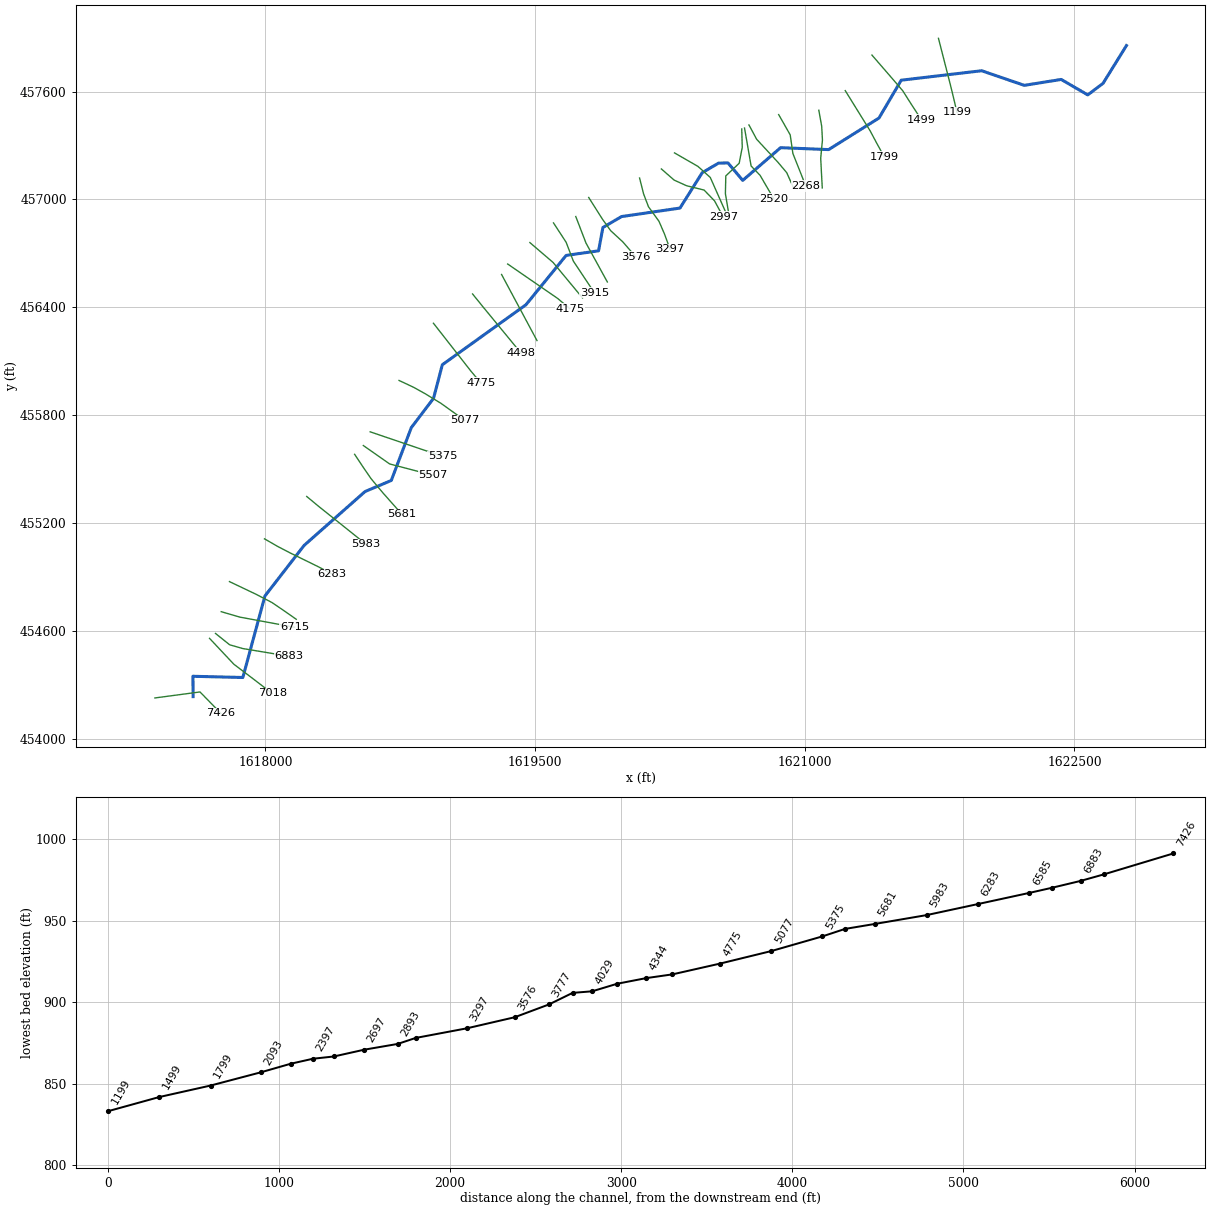
--- RockyFk.prj (project) ---

Proj Title=RockyFk
Current Plan=p01
Default Exp/Contr=0,0
English Units
Geom File=g01
Flow File=f01
Plan File=p01
BEGIN DESCRIPTION:
---------- MODELED AS PART OF WVEM CTP PROGRAM, 2025----------
Stream Name: Rocky Fork
Flood Zone: AFH
Marshall County, WV
HEC-RAS Version: RAS 6.6
Vertical Datum: NAVD88
Projection: NAD 1983 StatePlane West Virginia N FIPS 4701 (US Feet)
Terrain: 1-meter West Virginia FEMA R3 South Central (collected 2018-2019)
Land Use: 2024 NLCD
Hydrologic Method:
Duda et al., "Estimation of magnitude and frequency of floods for rural, unregulated streams in and near Virginia and West Virginia." September 8, 2025.
Additional Model Notes:
None
END DESCRIPTION:
DSS Export Rating Curves= 0
DSS Export Rating Curve Sorted= 0
DSS Export Volume Flow Curves= 0
DXF OffsetX= 0
DXF OffsetY= 0
DXF ScaleX= 0
DXF ScaleY= 0

--- RockyFk.p01 (plan) ---

Plan Title=Floodplain
Program Version=6.60
Short Identifier=Floodplain
Geom File=g01
Flow File=f01
Subcritical Flow
K Sum by GR= 0
Std Step Tol= 0.01
Critical Tol= 0.01
Num of Std Step Trials= 20
Max Error Tol= 0.3
Flow Tol Ratio= 0.001
Split Flow NTrial= 30
Split Flow Tol= 0.02
Split Flow Ratio= 0.02
Log Output Level= 0
Friction Slope Method= 1
Unsteady Friction Slope Method= 2
Unsteady Bridges Friction Slope Method= 1
Parabolic Critical Depth
Global Vel Dist= 0 , 0 , 0
Global Log Level= 0
CheckData=False
Encroach Param=-1 ,0,0, 0
Flow Ratio Tolerance=0.1
Flow Ratio Min Ratio=0.5
Flow Ratio Max Ratio=4
Flow Ratio Max Iterations= 10
Mapping Interval=1HOUR
Computation Time Step Use Courant=        0
Computation Time Step Use Time Series=    0
Computation Time Step Count To Double=0
Computation Time Step Max Doubling=0
Computation Time Step Max Halving=0
Computation Time Step Residence Courant=0
Run HTab= 0
Run UNet= 0
Run Sediment= 0
Run PostProcess= 0
Run WQNet= 0
Run RASMapper=-1
UNET Theta= 0
UNET Theta Warmup= 0
UNET ZTol= 0
UNET ZSATol= 0
UNET MxIter= 0
UNET Max Iter WO Improvement= 0
UNET MaxInSteps= 0
UNET DtIC= 0
UNET DtMin= 0
UNET MaxCRTS= 0
UNET WFStab= 0
UNET SFStab= 0
UNET WFX= 1
UNET SFX= 1
UNET Gravity=32.17405
UNET 1D Methodology=Finite Difference
UNET DSS MLevel= 1
UNET Pardiso=0
UNET DZMax Abort= 0
UNET Use Existing IB Tables= 0
UNET Froude Reduction=False
UNET Froude Limit= 0
UNET Froude Power= 0
UNET D1 Cores= 0
UNET WindReference=Eulerian
UNET WindDragFormulation=Hsu (1988)
UNET D2 Coriolis=0
UNET D2 Cores= 0
UNET D2 Theta= 1
UNET D2 Theta Warmup= 1
UNET D2 Z Tol= 0.01
UNET D2 Volume Tol= 0.01
UNET D2 Max Iterations= 20
UNET D2 Advanced Convergence=0
UNET D2 WS Max Tol=0.15
UNET D2 WS RMS Tol=0.002
UNET D2 WS Stall Tol=1
UNET D2 Equation= 0
UNET D2 RampUpFraction=0.1
UNET D2 TimeSlices= 1
UNET D2 Turbulence Formulation=Non-Conservative (original)
UNET D2 Eddy Viscosity=0.3
UNET D2 Transverse Eddy Viscosity=0.1
UNET D2 Smagorinsky Mixing=0
UNET D2 BCVolumeCheck=0
UNET D2 Cores=0
UNET D2 SolverType=PARDISO (Direct)
UNET D2 Minimum Iterations= 3
UNET D2 Maximum Iterations= 30
UNET D2 Restart Number= 10
UNET D2 Relaxation Coeff=1.3
UNET D2 SOR Precondition Iterations= 10
UNET D2 ILUT Maximum Fill= 8
UNET D2 ILUT Tolerance=1E-08
UNET D2 Convergence Tolerance=0.00001
PS Theta= 1
PS WS Tol= 0.01
PS Volume Tol= 0.01
PS Max Iterations= 20
PS Equation= 0
PS Advance Time Step=-1
PS Target Courant=0.9
PS Time Slices= 1
PS Iterate With 2D=0
PS Project Initial WSE from DS=-1
PS Ramp Up Initial WSE from US=-1
PS Cores=0
UNET D1D2 MaxIter= 0
UNET D1D2 ZTol=0.01
UNET D1D2 QTol=0.1
UNET D1D2 MinQTol=1
Write IC File= 0
Write IC File at Fixed DateTime=0
Write IC File at Sim End=0
Echo Input=False
Echo Parameters=False
Echo Output=False
Write Detailed= 0
HDF Write Warmup=0
HDF Write Time Slices=0
HDF Flush=0
HDF Compression= 1
HDF Chunk Size= 1
HDF Spatial Parts= 1
HDF Use Max Rows=0
HDF Fixed Rows= 1
Calibration Method= 0
Calibration Iterations= 20
Calibration Max Change=0.05
Calibration Tolerance=0.2
Calibration Maximum=1.5
Calibration Minimum=0.5
Calibration Optimization Method= 1
WQ AD Non Conservative
WQ ULTIMATE=-1
WQ Max Comp Step=1HOUR
WQ Output Interval=15MIN
WQ Output Selected Increments= 0
WQ Create Restart=0
WQ Fixed Restart=0
WQ System Summary=0
WQ Write To DSS=0
Sorting and Armoring Iterations= 10
XS Update Threshold= 0.02
Bed Roughness Predictor= 0
Processes Affected by Predictor=Sediment Only
Hydraulics Update Threshold= 0.02
Energy Slope Method= 1
Volume Change Method= 1
Sediment Retention Method= 0
Sediment TS Multiplier= 1
Warm Up Method= 0
XS Weighting Method= 0
Number of US Weighted Cross Sections= 1
Number of DS Weighted Cross Sections= 1
Upstream XS Weight=0
Main XS Weight=1
Downstream XS Weight=0
Number of DS XS's Weighted with US Boundary= 1
Upstream Boundary Weight= 1
Weight of XSs Associated with US Boundary= 0
Number of US XS's Weighted with DS Boundary= 1
Downstream Boundary Weight= 0.5
Weight of XSs Associated with DS Boundary= 0.5
Percentile Method= 0
Sediment Output Level= 3
Mass or Volume Output= 0
Output Increment Type= 1
Profile and TS Output Increment= 1
Transport Output Increment 1
XS Output Flag= 0
XS Output Increment= 10
Read HDF5 Sediment Hotstart= 0
Sediment Hotstart Type= 0
Write Gradation File= 0
Read Gradation Hotstart= 0
Write HDF5 File= 1
Write Binary Output= 1
Write DSS Sediment File= 0
DSS Sediment Output Type= 1
SV Curve= 0
Specific Gage Flag= 0
Subcell Erosion Methods= 0
Subcell Deposition Methods= 0
Advection Scheme= 1
Matrix Solver= 0
Implicit Weighting Factor= 1
Maximum Outer Loop Convergence Iterations= 5
Convergence Maximum Absolute= 0.001
Convergence RMSE= 0.0001
Grain Fractions Max Abs Error= 0.001
Max Subgrid Regions= 1
Max Subgrid Length Scale= 3.402823E+38
Initial Layer Thickness= 3
Min Layer Thickness= 0.1
Max Layer Thickness= 6
Number of Layers= 5

--- RockyFk.f01 (steady flow) ---

Flow Title=Flow
Program Version=6.60
Number of Profiles= 1
Profile Names=P100yr
River Rch & RM=RockyFk,Main            ,7426
     960
River Rch & RM=RockyFk,Main            ,3777
    1070
Boundary for River Rch & Prof#=RockyFk,Main            , 1
Up Type= 0
Dn Type= 3
Dn Slope=0.045
DSS Import GetInterval= 0
DSS Import GetPeak= 0
DSS Import FillOption= 0

--- RockyFk.g01 (geometry) ---

Geom Title=Geometry
Program Version=6.60

River Reach=RockyFk         ,Main
Reach XY= 30
1617597.30307365454234.1104405791617596.40335042454347.216056909
     1617874.058      454340.437     1617996.894      454793.985
     1618215.021      455075.443     1618554.057      455375.003
1618699.76073525455436.464437198     1618811.044      455730.294
     1618934.893       455893.62     1618983.659      456080.168
     1619449.121       456414.141619672.48859455456688.496546148
1619852.81180427 456714.014735411619876.99345857456843.677464288
     1619980.643      456904.538     1620305.747      456951.755
     1620429.275      457148.451      1620520.16      457201.776
     1620572.523      457202.994     1620654.846      457105.792
      1620865.39      457287.696     1621132.669      457277.044
     1621412.647       457452.57     1621536.496      457663.113
     1621983.901      457715.749     1622220.762      457634.473
1622426.31366061 457667.30345335     1622574.119      457581.319
     1622659.079      457645.513     1622789.391      457855.799

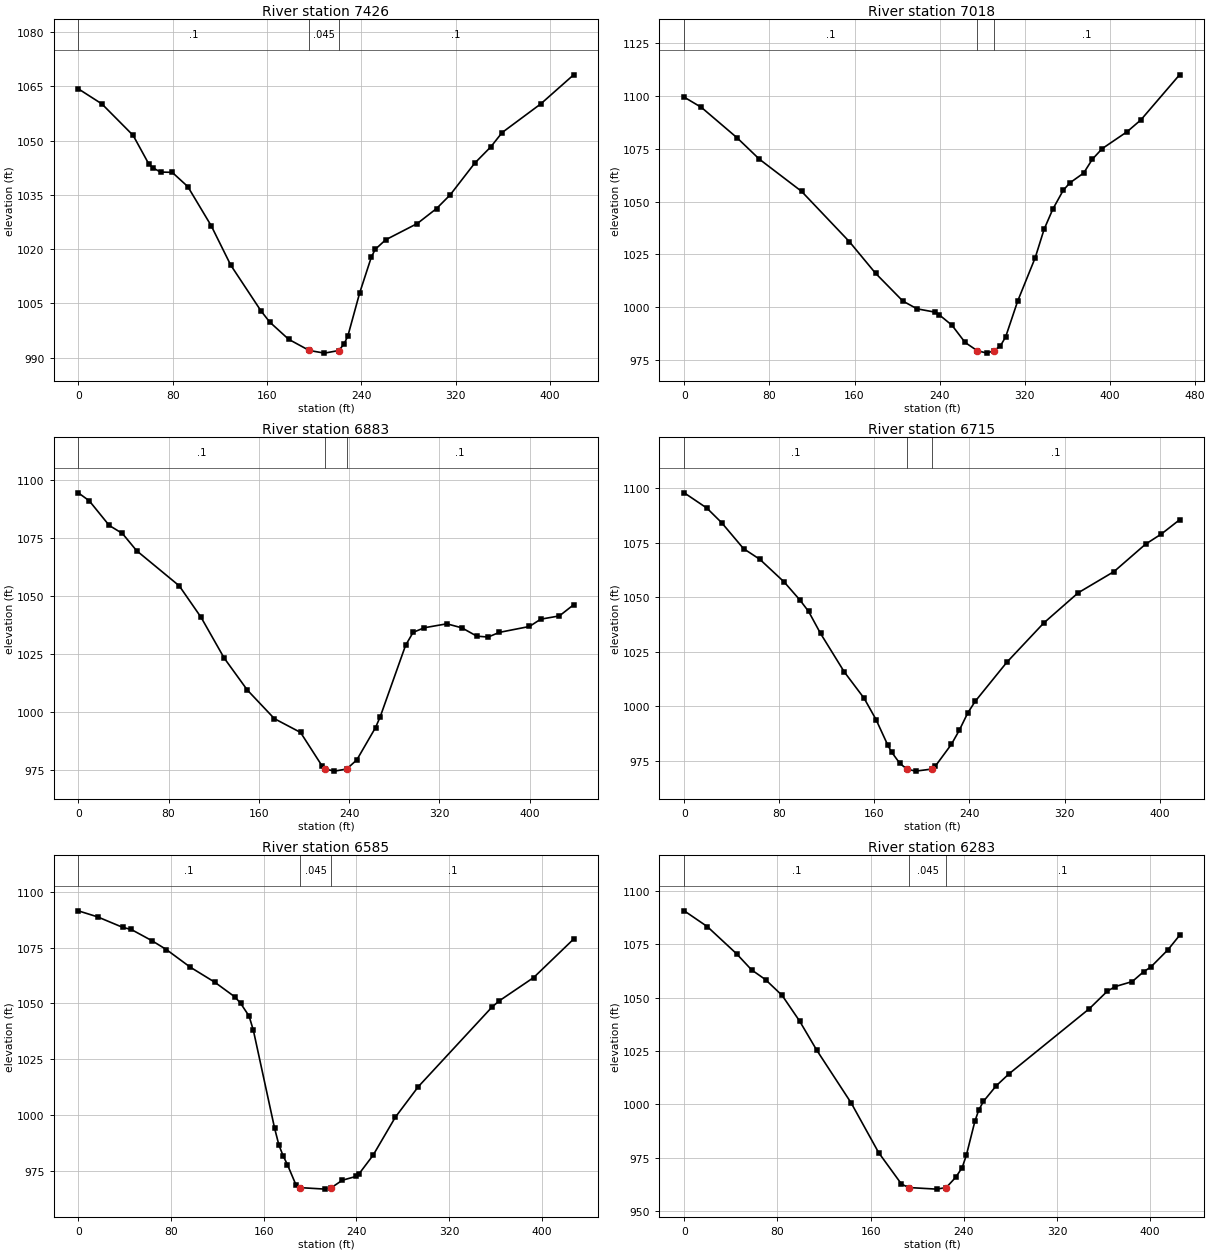
Type RM Length L Ch R = 1 ,7426    ,421.3,408,394.6
XS GIS Cut Line= 3
1617384.64233832454226.5952021441617635.63290913454260.069750144
1617752.07508315454140.838542016
#Sta/Elev= 30
       0 1064.33      20 1060.15    46.5 1051.44    59.7 1043.58      63 1042.51
    69.7 1041.31    79.6 1041.23    92.8 1037.29   112.7 1026.44   129.2 1015.58
   154.9 1002.89   162.3  999.81   178.3  995.06   195.8  991.96   208.7  991.23
  220.76  991.95   225.2  993.71   228.5  995.96   238.5 1007.86   248.4 1017.78
   251.7 1019.93   260.5 1022.56   287.4 1027.08   303.7 1031.22   315.3 1035.02
   336.1 1043.79   349.7 1048.28   359.3 1052.24     392 1060.15   419.9  1068.2
#Mann= 3 ,0,0
       0      .1       0   195.8    .045       0  220.76      .1       0
Bank Sta=195.8,220.76
XS Rating Curve= 0 ,0
Exp/Cntr=0.3,0.1

Type RM Length L Ch R = 1 ,7018    ,132.2,135,139.7
XS GIS Cut Line= 4
1617688.68935943454558.2699870911617823.96320166454414.270121296
1617930.12214098454333.9619173841618037.04218223454251.941063819
#Sta/Elev= 30
       0 1099.32    16.2 1094.47    49.7  1080.1    70.7 1069.97   110.2 1054.83
   155.1 1031.06   179.8 1016.07   205.4 1002.96   218.7  999.29   235.2  997.75
   239.3  996.58   251.6   991.5   263.9  983.39   275.3979.4933   284.5  978.34
  290.81 979.493   296.9  981.61     302     986   313.3 1002.92   329.8 1023.46
   338.1 1036.82   346.3 1046.38   356.1 1055.28   362.3  1058.8   375.3 1063.44
   383.5    1070   392.7 1074.99   416.1 1082.98     429 1088.54   465.4 1109.88
#Mann= 3 ,-1,0
       0      .1       0   275.3    .045       0  290.81      .1       0
Bank Sta=275.3,290.81
XS Rating Curve= 0 ,0
Exp/Cntr(USF)=0,0
Exp/Cntr=0.3,0.1

Type RM Length L Ch R = 1 ,6883    ,168.6,168.2,168.1
XS GIS Cut Line= 6
1617721.71389967454585.6111397591617800.66781001454522.412775338
1617873.22278301454501.5118985031617971.86891118454485.112653092
1618045.85334326 454472.813137011618132.16878742454458.463756248
#Sta/Elev= 30
       0  1094.4     9.7 1090.96    27.4 1080.34    39.1 1076.86    51.7 1069.44
    89.5 1054.27   108.8 1040.72   129.3 1023.14   149.8 1009.35   173.8     997
     197  991.05   216.3  976.44  219.03975.2557     227  974.36  237.87975.2551
   246.9  979.21   263.5  993.17   267.7  997.89   290.1 1028.59   296.8 1034.22
   306.8 1036.21   326.7  1037.9     340 1036.17   353.3 1032.57   363.3  1032.2
   373.2  1034.2   399.9 1036.75   409.9 1039.89   426.5 1041.32   439.1 1046.12
#Mann= 3 ,-1,0
       0      .1       0  219.03    .045       0  237.87      .1       0
Bank Sta=219.03,237.87
XS Rating Curve= 0 ,0
Exp/Cntr(USF)=0,0
Exp/Cntr=0.3,0.1

Type RM Length L Ch R = 1 ,6715    ,134.9,130.1,127.8
XS GIS Cut Line= 3
1617753.56716991454706.5726704521617857.70436078454676.254247795
1618160.88858735454620.231075493
#Sta/Elev= 30
       0 1097.91    19.1 1090.88    31.5 1084.19    49.9 1072.29    63.6 1067.39
    84.1 1056.97    97.4 1048.66   104.6  1043.5   114.7 1033.35   134.7 1015.67
   151.4 1003.57   161.4  993.82   171.4  981.94   174.7  978.74   181.4  973.72
  187.33971.0884   194.7  970.14  208.38 971.087   211.4   972.5   224.8  982.43
   231.4  988.83   238.6  996.86   244.8 1002.15   271.5 1020.14   302.5 1038.13
   331.5 1052.01   361.7 1061.77   388.2 1074.34   401.6 1079.04   416.8 1085.52
#Mann= 3 ,-1,0
       0      .1       0  187.33    .045       0  208.38      .1       0
Bank Sta=187.33,208.38
XS Rating Curve= 0 ,0
Exp/Cntr(USF)=0,0
Exp/Cntr=0.3,0.1

Type RM Length L Ch R = 1 ,6585    ,300.8,301.7,303.1
XS GIS Cut Line= 6
1617799.57168359454873.8733585031617878.56890093454836.247449502
1617946.28103584454803.9968578371618035.11550385454757.956923679
1618097.92049634454715.4035310891618170.91247635454664.422333837
#Sta/Elev= 30
       0 1091.39    16.6  1088.7    38.4 1083.99    45.7 1083.06    63.7    1078
      76 1074.09    96.6 1066.23   117.8 1059.49   135.1 1052.94     140 1050.14
   147.4 1044.34   151.1 1037.98   169.4  994.28   173.1   986.8   176.7  982.02
   180.5  977.96   187.8  969.02  191.26967.7233   213.2  967.05  218.51967.7254
   227.8  971.01   239.6  972.72   242.5  974.03   254.4  982.18   273.6  999.17
   293.4  1012.8     357 1048.37   363.5 1051.24     393 1061.58   427.5 1078.77
#Mann= 3 ,-1,0
       0      .1       0  191.26    .045       0  218.51      .1       0
Bank Sta=191.26,218.51
XS Rating Curve= 0 ,0
Exp/Cntr(USF)=0,0
Exp/Cntr=0.3,0.1

Type RM Length L Ch R = 1 ,6283    ,307.3,300,297.1
XS GIS Cut Line= 6
 1617994.2717535455111.7846280931618070.32081401455068.143639252
1618136.90401417455033.5823566761618226.65941209454989.492221758
1618293.97620659454956.4247025851618371.35334842454915.486792341
#Sta/Elev= 30
       0 1090.71    19.8 1083.32    44.9 1070.59    57.8 1063.03    69.8 1058.43
    84.1    1051      99 1039.05   113.7  1025.4   143.3 1000.61   166.9   977.3
   186.5  962.55  192.69960.9308   216.6  960.18  224.95960.9294   233.1  965.76
   238.6  970.27   242.2  976.11   249.5  991.98   252.7  997.08   256.8 1001.31
   267.8 1008.63   278.8 1014.25   347.9 1044.87   363.2 1053.03   370.1  1055.2
   384.6 1057.53   394.3 1062.12   400.4 1064.28   415.2 1072.42   425.2 1079.19
#Mann= 3 ,-1,0
       0      .1       0  192.69    .045       0  224.95      .1       0
Bank Sta=192.69,224.95
XS Rating Curve= 0 ,0
Exp/Cntr(USF)=0,0
Exp/Cntr=0.3,0.1

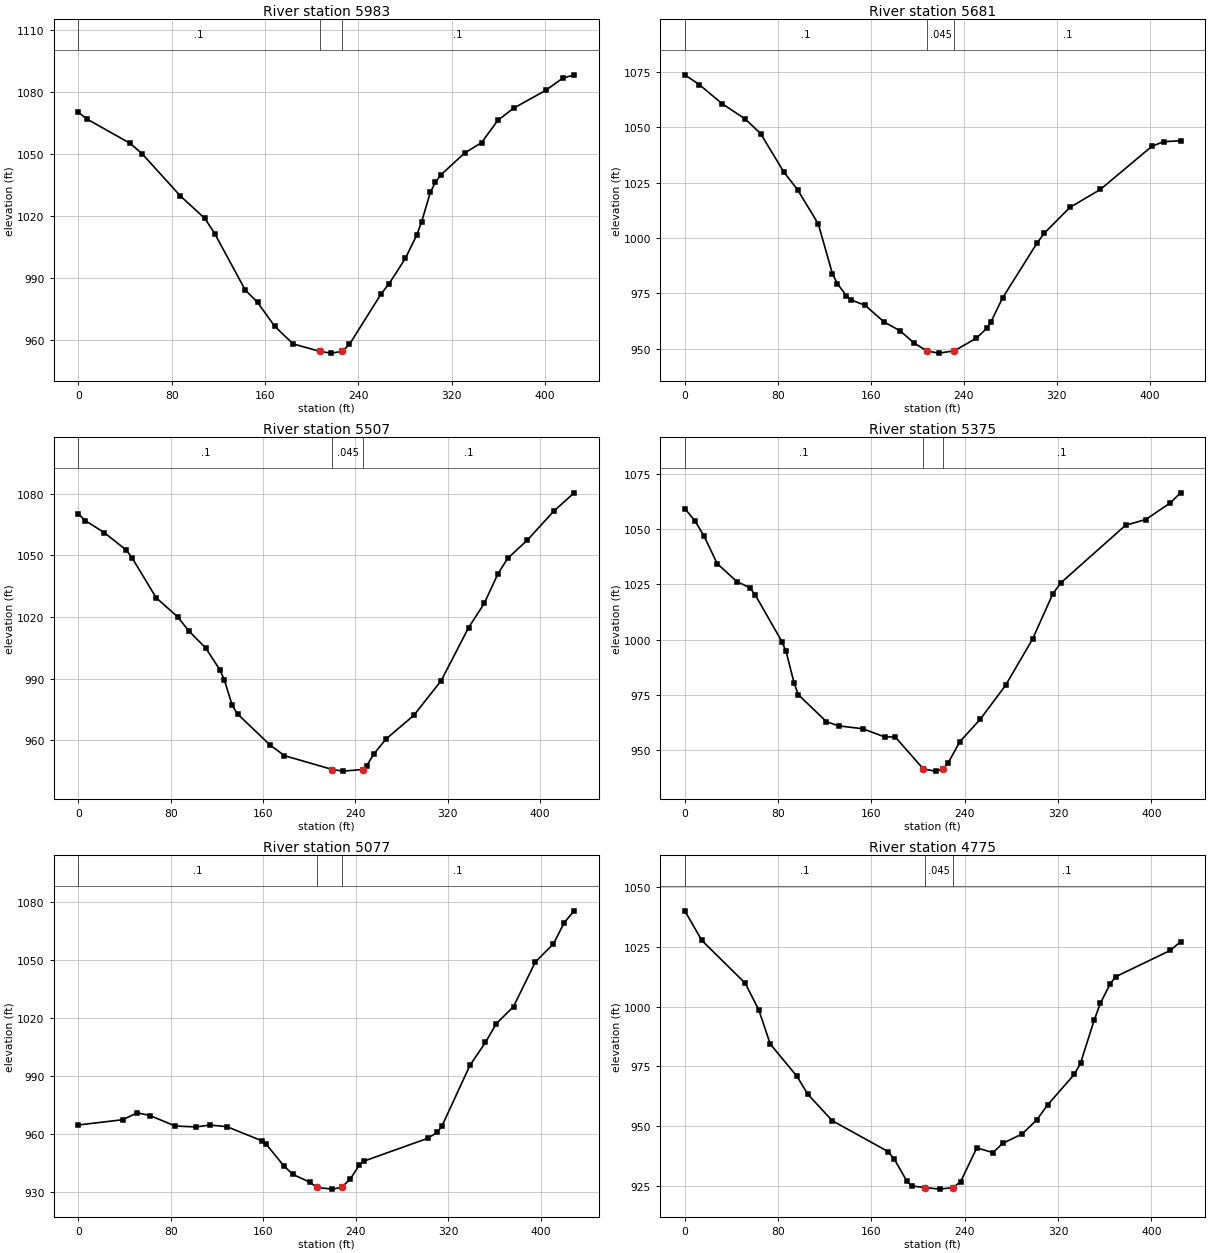
Type RM Length L Ch R = 1 ,5983    ,303.4,302.8,300.1
XS GIS Cut Line= 6
1618229.46189992455347.3054825071618296.86465226455291.489977345
1618355.44622801455244.6580500011618433.55433951455182.215589583
1618492.13591526455135.3836622541618560.48092292455080.746304333
#Sta/Elev= 30
       0 1070.07     7.3 1066.78    44.2 1055.05    54.5 1050.05    87.5 1029.49
   108.5  1018.6   116.9 1011.28   143.1  983.91   153.6  978.01   168.2  966.48
   184.1  957.88  207.22954.2123   216.7  953.41  225.98 954.212   232.4  957.64
   259.7  982.24   266.3  986.93   280.3  999.26   290.2 1010.75   294.3 1017.09
   301.7 1031.21     306 1036.09   310.6 1039.63   331.1 1050.29   345.6 1055.32
   359.6 1066.14   373.1    1072   400.6 1080.63   415.1  1086.5     425 1088.16
#Mann= 3 ,-1,0
       0      .1       0  207.22    .045       0  225.98      .1       0
Bank Sta=207.22,225.98
XS Rating Curve= 0 ,0
Exp/Cntr(USF)=0,0
Exp/Cntr=0.3,0.1

Type RM Length L Ch R = 1 ,5681    ,167.2,173.8,182.1
XS GIS Cut Line= 6
1618495.75401826455582.0635431711618544.59283134455508.425567091
1618587.46315242455446.2012820841618651.56768301455369.392708674
1618701.32447326 455313.274710671618759.37422593455247.803384915
#Sta/Elev= 30
       0 1073.71    12.4 1069.33    32.1 1060.66    51.8 1053.83    65.2 1047.17
    85.3 1029.71      97 1021.82   114.8 1006.38     127  983.84   131.3  979.34
     139  973.92   143.1  971.97   154.9  969.67   171.3  962.11   185.3  958.03
   196.8  952.72  208.14948.9835   218.4  947.99  231.68948.9828   250.5  954.66
   259.8  959.18   263.4  962.15   273.3  972.89     303  997.71   309.2 1002.17
   331.2  1013.8   357.4 1021.91   401.9 1041.47   411.8 1043.49   426.5 1043.94
#Mann= 3 ,-1,0
       0      .1       0  208.14    .045       0  231.68      .1       0
Bank Sta=208.14,231.68
XS Rating Curve= 0 ,0
Exp/Cntr(USF)=0,0
Exp/Cntr=0.3,0.1

Type RM Length L Ch R = 1 ,5507    ,132.3,131.5,130.3
XS GIS Cut Line= 3
1618544.30418349455630.8506764351618690.76999343455528.324609477
1618933.25227877455464.856091837
#Sta/Elev= 30
       0 1070.29     6.1 1066.93    22.6 1061.09    41.5 1052.61    46.4 1048.98
    67.4 1029.43    85.9 1020.17    95.6 1013.31   110.4 1004.87   122.5  994.38
   126.5  989.31   133.3  976.94     138  972.72     166   957.7   178.5  952.49
  220.01945.7381   229.4  944.95  246.21945.7377   249.8   947.6   255.9  953.32
   266.7  960.72   290.5   972.1   314.2  988.98     338 1014.89   351.5 1026.61
   363.4 1041.09   371.9 1048.63   388.8 1057.46   411.8 1071.62   429.4 1080.52
#Mann= 3 ,-1,0
       0      .1       0  220.01    .045       0  246.21      .1       0
Bank Sta=220.01,246.21
XS Rating Curve= 0 ,0
Exp/Cntr(USF)=0,0
Exp/Cntr=0.3,0.1

Type RM Length L Ch R = 1 ,5375    ,299.7,298.2,296
XS GIS Cut Line= 6
1618582.18822859455707.163686678  1618665.012538 455678.94294259
1618736.03765842455654.8507991731618830.73760025455622.727503836
1618901.76272067455598.6350323411618984.62508775455570.527477011
#Sta/Elev= 30
       0 1059.45     8.6 1053.89    16.3 1047.19    27.8 1034.45    44.8 1026.24
    55.6 1023.61    60.3 1020.34    83.3  999.05    86.8  994.65    93.7  980.37
    97.2  975.11   121.4  962.81   131.8  960.92   152.6   959.6   171.5  955.85
   180.3  955.94  204.54 941.329   214.9  940.39  221.35941.3307   225.8  944.17
   235.7  953.71   253.1  963.81     275  979.31   298.1 1000.27   315.4 1020.71
   322.3 1025.74   377.8 1051.86   395.1 1054.45   415.9 1061.91     425 1066.56
#Mann= 3 ,-1,0
       0      .1       0  204.54    .045       0  221.35      .1       0
Bank Sta=204.54,221.35
XS Rating Curve= 0 ,0
Exp/Cntr(USF)=0,0
Exp/Cntr=0.3,0.1

Type RM Length L Ch R = 1 ,5077    ,303.1,301.8,293.7
XS GIS Cut Line= 6
1618742.76467909455992.9390337621618823.99515967455954.748493344
1618890.35723168455917.8456799981618976.16185009 455865.52262193
1619037.11809301455821.8422630881619108.21736026 455770.89485842
#Sta/Elev= 30
       0  964.66    38.2  967.37    51.1  970.97    61.9  969.57    83.7  964.12
   101.5  963.65   114.1  964.61   128.5  963.78   158.6  956.48   162.3  954.79
   177.6  943.51   185.3  939.12   200.3  934.94  206.13932.3016   219.6  931.41
  227.65932.3035   235.3  936.79   242.9  943.86   246.8   945.9   302.3  957.79
   310.4   960.9   314.4  964.12   338.6  995.58     352 1007.44   361.4 1017.18
   376.3 1026.04   395.1  1049.1   410.8 1058.56   420.2  1069.6   428.7 1075.66
#Mann= 3 ,-1,0
       0      .1       0  206.13    .045       0  227.65      .1       0
Bank Sta=206.13,227.65
XS Rating Curve= 0 ,0
Exp/Cntr(USF)=0,0
Exp/Cntr=0.3,0.1

Type RM Length L Ch R = 1 ,4775    ,276.4,276.7,277
XS GIS Cut Line= 6
 1618934.1557005456311.2658249291618988.08242993456242.359138593
1619034.30576268456183.2962645891619095.93654492456104.545765921
1619142.15954959456045.4828919171619198.44224542455978.419705838
#Sta/Elev= 30
       0    1040    14.6 1027.64    51.8 1009.74    63.5  998.52    73.2  984.37
    96.2  970.79   105.5  963.32   126.4  952.27   174.3  939.37   179.7  936.12
   190.3   927.1   194.4  925.01   205.9  924.32   218.4  923.67  229.89  924.31
   236.4  926.73   250.4  940.94   264.2  938.93   272.5  942.78   289.2  946.73
   301.7  952.57   311.2  958.97     334  971.66   339.3  976.34   350.9  994.18
   356.3 1001.36   364.8 1009.54   369.5 1012.47   416.1 1023.42   425.1 1027.08
#Mann= 3 ,0,0
       0      .1       0   205.9    .045       0  229.89      .1       0
Bank Sta=205.9,229.89
XS Rating Curve= 0 ,0
Exp/Cntr(USF)=0,0
Exp/Cntr=0.3,0.1

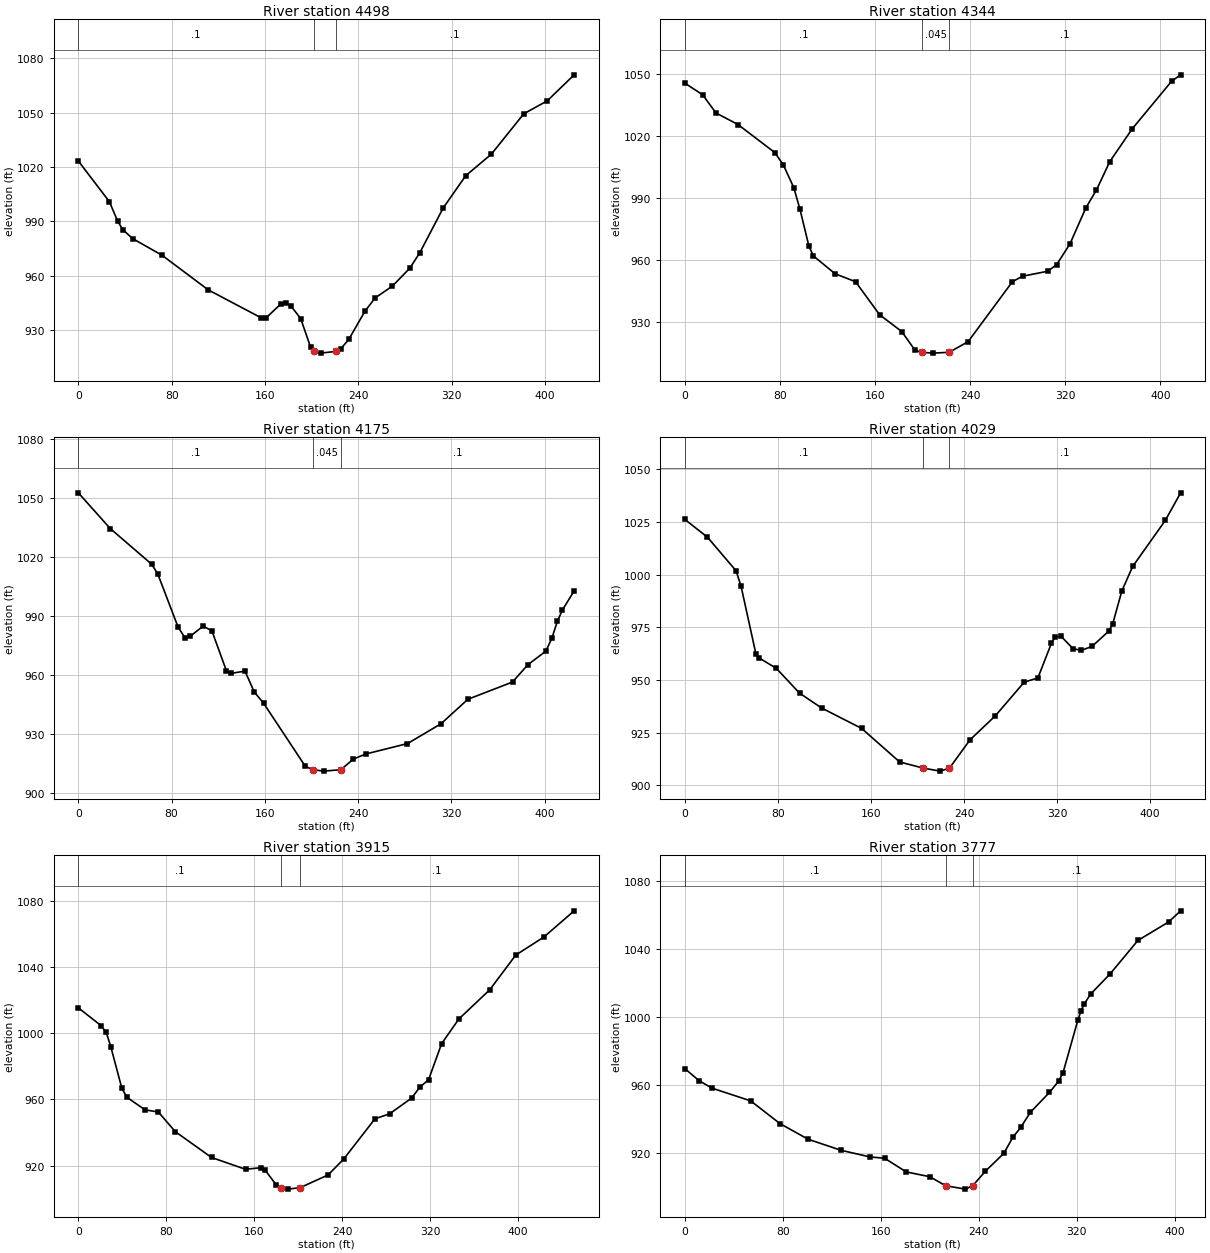
Type RM Length L Ch R = 1 ,4498    ,156.2,154.2,152.1
XS GIS Cut Line= 6
  1619151.940975456474.0459135341619206.90182308456405.956154705
1619254.55100599456348.0379634511619318.08303117456270.813052283
  1619365.731886456212.8942048711619421.32199791456145.321833448
#Sta/Elev= 30
       0 1023.29    26.6  1000.8    33.8  989.92    38.1  985.34    46.5  980.42
    71.8  971.16   111.3  952.08   156.6  936.66   160.9  936.56   173.6   944.3
   177.9  944.79   182.1  943.23   190.6  936.22   199.1  920.31     202918.0458
   207.6   917.1  220.55 918.042   224.8  919.38   231.8  924.65   245.7  940.29
   254.4  947.61   269.1  954.08   284.1     964   292.6  972.48   312.7  997.27
     332  1015.1   354.1 1027.11   381.8 1049.36   401.9 1056.51     425  1070.9
#Mann= 3 ,-1,0
       0      .1       0     202    .045       0  220.55      .1       0
Bank Sta=202,220.55
XS Rating Curve= 0 ,0
Exp/Cntr(USF)=0,0
Exp/Cntr=0.3,0.1

Type RM Length L Ch R = 1 ,4344    ,163.2,169,174.3
XS GIS Cut Line= 2
1619313.24853758456582.3413957551619510.24505195 456214.71221281
#Sta/Elev= 30
       0 1045.68      15 1040.03    26.2 1031.22    44.8 1025.58    75.7 1012.02
      83 1005.92    91.7  994.99    96.9  984.48   104.4  966.65   108.1  961.94
   126.4  953.26   143.6  949.42   163.9  933.39   182.5  925.26   193.7  916.16
   199.3  915.18   208.6  914.79   222.4  915.18   238.4  920.39   275.6  949.42
   284.1  952.07   305.4  954.49   312.8   957.7     324  967.73   337.4  985.23
   346.3  993.87   357.5 1007.61   376.2 1023.38   409.6 1046.64   417.1 1049.69
#Mann= 3 ,0,0
       0      .1       0   199.3    .045       0   222.4      .1       0
Bank Sta=199.3,222.4
XS Rating Curve= 0 ,0
Exp/Cntr(USF)=0,0
Exp/Cntr=0.3,0.1

Type RM Length L Ch R = 1 ,4175    ,148.5,146.1,141.7
XS GIS Cut Line= 6
1619347.10467775456640.6414785091619419.16424492456591.006079093
1619480.92921326456548.4612166731619563.28305118456491.734952167
1619625.04834759456449.1904178411619692.38285859   456392.695124
#Sta/Elev= 30
       0  1052.6    27.4 1034.46      63 1016.33    68.3 1011.21    85.6  984.43
    91.4  979.13      96   979.8   107.1  984.97   114.6  982.54     127  962.34
     131  960.97     143  962.11   150.9  951.56   158.9  945.87   194.7  913.83
  200.94912.0684   210.7  911.35  225.24912.0692     236  917.47   246.5  920.03
   282.4  925.33   311.2   935.4   334.2  947.81   372.5  956.57   385.7  965.37
   401.1  972.23   406.2  978.68     411  987.39   415.3  993.11   425.4 1002.85
#Mann= 3 ,-1,0
       0      .1       0  200.94    .045       0  225.24      .1       0
Bank Sta=200.94,225.24
XS Rating Curve= 0 ,0
Exp/Cntr(USF)=0,0
Exp/Cntr=0.3,0.1

Type RM Length L Ch R = 1 ,4029    ,115.8,114.5,111.5
XS GIS Cut Line= 3
1619470.69187847456759.8517027181619600.00100078456649.064215476
1619763.33056673 456452.05380313
#Sta/Elev= 30
       0 1026.23    19.4 1017.81    44.1 1001.82    48.4  994.41    61.2  962.16
    63.7  960.51    78.7  955.51    98.6  943.76   117.6  936.69     152     927
   184.7  911.06  205.13908.1415   219.6  906.72  227.51908.1431   245.2   921.6
   266.9  932.96   291.8  948.99   303.5  950.93   315.1  967.37   318.3  970.35
   323.5  970.69   333.7  964.86   340.8  964.04   350.1  965.95   364.6  973.26
   367.9  976.78   375.7  992.31     385 1003.88     413 1025.71   426.2 1038.84
#Mann= 3 ,-1,0
       0      .1       0  205.13    .045       0  227.51      .1       0
Bank Sta=205.13,227.51
XS Rating Curve= 0 ,0
Exp/Cntr(USF)=0,0
Exp/Cntr=0.3,0.1

Type RM Length L Ch R = 1 ,3915    ,130.8,138,137.7
XS GIS Cut Line= 4
1619602.05592559456869.3607801771619672.45304114456761.345682734
1619712.40994419456656.9259439581619828.88397911456481.794938897
#Sta/Elev= 30
       0 1015.36    20.6 1004.64    25.4 1000.47    29.5  991.97    39.6  966.66
    44.3  961.21    60.8  953.64    72.8  952.39    88.2  940.51   121.2  924.88
   152.1  917.74   166.2   918.7   169.7  917.45   180.2  908.18   184.5906.6509
   190.7  905.75  201.83906.6503   227.3  914.34   241.5  923.99   269.9  948.28
   283.2  951.27   303.2  960.79   310.8  967.48   318.6   971.8   330.5  993.67
   346.2 1008.61   374.3 1026.26   397.9 1047.21   423.7 1058.23   451.1    1074
#Mann= 3 ,-1,0
       0      .1       0   184.5    .045       0  201.83      .1       0
Bank Sta=184.5,201.83
XS Rating Curve= 0 ,0
Exp/Cntr(USF)=0,0
Exp/Cntr=0.3,0.1

Type RM Length L Ch R = 1 ,3777    ,194.2,200.3,198.4
XS GIS Cut Line= 3
 1619726.1102662456904.7304904381619782.67932829456757.594957118
1619901.52235143456540.793525599
#Sta/Elev= 30
       0   969.7    11.6  962.61    22.2  958.18    53.8  950.67    77.8  937.24
   100.7  928.07   127.6  921.55   151.5   917.6   163.1   916.9   180.8  908.82
   200.1  905.98     213  900.68   229.1  898.67   235.2 900.738   245.4  909.18
   260.5  919.71   267.8  929.11   274.5  935.22   282.3  944.02   297.8  955.65
   305.3  962.33   308.9  967.34   320.9  998.08   323.4 1003.47     326 1007.53
   331.4 1013.58   347.5 1025.65     370  1045.2     395 1056.05   404.9 1062.66
#Mann= 3 ,-1,0
       0      .1       0     213    .045       0   235.2      .1       0
Bank Sta=213,235.2
XS Rating Curve= 0 ,0
Exp/Cntr(USF)=0,0
Exp/Cntr=0.3,0.1

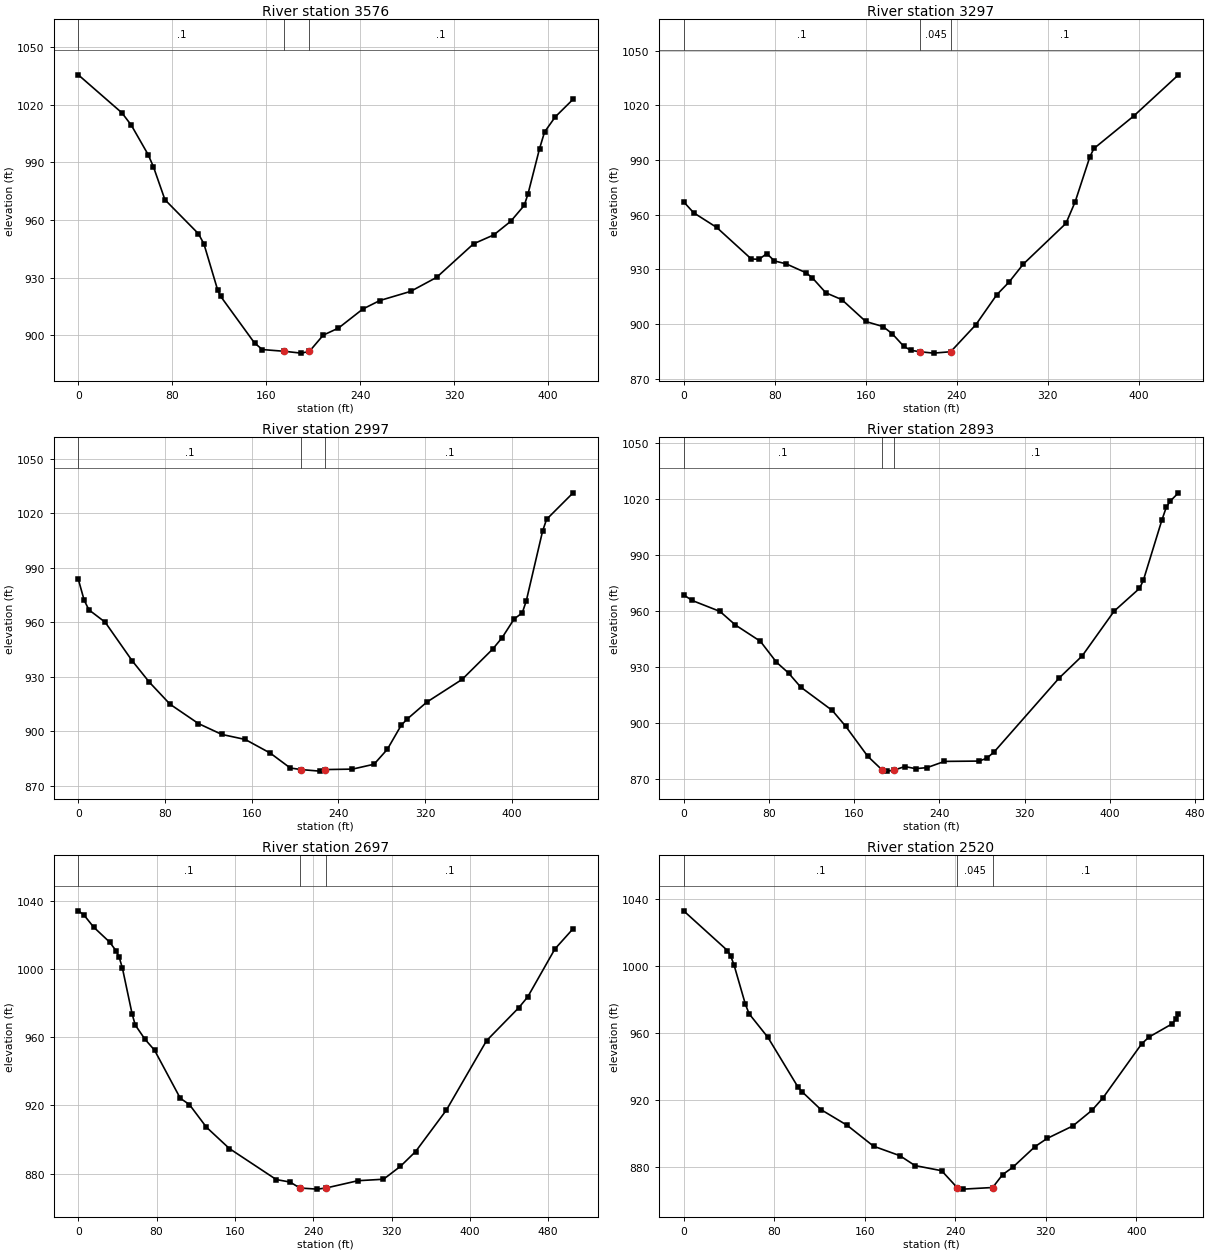
Type RM Length L Ch R = 1 ,3576    ,279.8,279.4,282.3
XS GIS Cut Line= 5
1619798.04825241457010.6461322681619874.40737515456889.976167133
  1619920.281681456825.9659110011619988.36159734456763.095301837
1620058.40443626456681.954716086
#Sta/Elev= 30
       0 1035.45    37.2 1015.67    45.2 1009.23    59.5  993.97      64  987.66
    73.8  970.53   102.3  952.88     107  947.59   118.7  923.62   121.3  920.29
   150.1  896.08   156.8  892.67   175.6  891.77   189.7  890.82   196.8   891.7
   208.6  900.16   221.6  903.85   242.3  913.73   256.8  918.15     283   922.9
   305.2  930.21   336.6  947.62   353.8  952.24   368.3  959.34   379.8   967.6
     383  973.58   392.8  997.06   397.1 1005.75   406.2 1013.59   421.4 1022.75
#Mann= 3 ,-1,0
       0      .1       0   175.6    .045       0   196.8      .1       0
Bank Sta=175.6,196.8
XS Rating Curve= 0 ,0
Exp/Cntr(USF)=0,0
Exp/Cntr=0.3,0.1

Type RM Length L Ch R = 1 ,3297    ,287.2,299.9,302.7
XS GIS Cut Line= 6
1620080.96016543457118.9216899281620103.21569835457030.866091758
1620130.35507976456959.337035343  1620188.954372456878.077683419
1620219.76270933 456806.937405751620250.59040359 456722.37950401
#Sta/Elev= 30
       0  967.03     8.8  961.01    29.1  952.95    59.5  935.66    66.3   935.5
    73.1  938.63    79.8  934.59      90  933.03   107.5  928.14   113.2   925.3
     125  917.13   139.1  913.36   160.1  901.39   175.2  898.62   183.3  894.72
   193.4  887.87   199.5  885.61     208  884.78   219.7  884.04  234.76   884.8
   256.9  899.63   275.3  916.08     286  922.96   298.6  932.86   336.1   955.2
   344.2  967.05   357.2  991.87   360.7  996.27   395.7 1014.09     435 1036.66
#Mann= 3 ,-1,0
       0      .1       0     208    .045       0  234.76      .1       0
Bank Sta=208,234.76
XS Rating Curve= 0 ,0
Exp/Cntr(USF)=0,0
Exp/Cntr=0.3,0.1

Type RM Length L Ch R = 1 ,2997    ,109.2,104.1,101
XS GIS Cut Line= 6
1620202.24371551457169.3989511731620273.53523959 457107.13824892
1620342.71751593457075.925384834  1620439.820012457052.027794838
1620497.98885892456991.957376927 1620546.7295751456901.855851084
#Sta/Elev= 30
       0  983.81     5.4  972.31     9.8  966.94    24.8  960.13    49.7  938.91
    65.6  927.09    84.7  914.95   110.9   904.3   132.5  898.32   154.1  895.55
   177.2  888.02   195.6  879.85  205.51878.9795   222.6  878.12  228.04878.9797
     253  879.23   272.9  881.91   285.2  890.15     298   903.4   303.4  906.74
   321.6  916.12   354.2  928.64   382.4  945.32   391.1  951.62   402.2  961.91
   409.7  965.29   413.4   971.9   428.4  1010.2   432.1 1016.77   456.6 1031.38
#Mann= 3 ,-1,0
       0      .1       0  205.51    .045       0  228.04      .1       0
Bank Sta=205.51,228.04
XS Rating Curve= 0 ,0
Exp/Cntr(USF)=0,0
Exp/Cntr=0.3,0.1

Type RM Length L Ch R = 1 ,2893    ,214.4,195.9,183
XS GIS Cut Line= 4
1620275.15065631457258.7341881191620405.47810386457183.729227674
1620474.39840443457121.9694778161620564.23076785456919.521180525
#Sta/Elev= 30
       0  968.84     7.9  965.86    34.1  959.97    48.6   952.7      72  943.99
    87.1  932.79    98.5  926.96   109.8  919.49   139.5  906.95   152.1  898.47
   172.7  882.46   186.5  874.99   191.3  874.47  197.36874.9932   207.6  876.92
   217.7  875.79   228.5  876.36   244.8  879.68   277.1  879.85   284.3   881.3
   291.4  884.74   352.4  924.31     374  936.13     404  960.11   427.8  972.29
   431.4  976.55   448.8 1008.81   452.9 1015.64   456.5 1018.95   464.4 1023.47
#Mann= 3 ,-1,0
       0      .1       0   186.5    .045       0  197.36      .1       0
Bank Sta=186.5,197.36
XS Rating Curve= 0 ,0
Exp/Cntr(USF)=0,0
Exp/Cntr=0.3,0.1

Type RM Length L Ch R = 1 ,2697    ,147.2,177,194.2
XS GIS Cut Line= 6
1620649.30942242457391.7364329991620652.06794709457289.544380173
1620635.04435909457201.055383921  1620560.599298457130.753359169
1620558.37817384457031.3198309991620576.92439659456921.537242174
#Sta/Elev= 30
       0  1034.2     5.7 1031.82    15.6  1024.7      32 1015.87    38.5 1010.85
    41.8 1006.95    45.1 1000.54      55   973.7    58.2  967.21    68.1  958.88
    77.9  952.45   104.2  924.24   113.5  920.57   130.9  907.27   154.3  894.77
   202.3  876.54   216.3   875.1  226.42871.5892   244.1  870.94  253.04871.5891
   285.7  875.88   311.8  876.74     329  884.26   344.6  892.98     376  917.28
   417.1  958.04   449.9   977.3   459.1  983.67   486.9 1011.82   505.5 1023.71
#Mann= 3 ,-1,0
       0      .1       0  226.42    .045       0  253.04      .1       0
Bank Sta=226.42,253.04
XS Rating Curve= 0 ,0
Exp/Cntr(USF)=0,0
Exp/Cntr=0.3,0.1

Type RM Length L Ch R = 1 ,2520    ,123.2,123.1,122.6
XS GIS Cut Line= 4
1620664.74119918457397.1165438371620701.45183732457185.748696791
1620751.34526901457133.8534289981620827.26267258 457003.55349766
#Sta/Elev= 30
       0  1033.2    38.7 1009.47    41.6 1006.21    44.6 1000.65    54.6  977.24
    57.9   971.6    74.5   957.5   101.2  927.65   104.5  925.12   121.2   914.4
   144.5  904.95   167.8  892.47   191.1  886.78   204.4  880.89     228   877.8
  241.64 867.756   247.1  866.79  273.09867.7574   281.9  875.48   290.8   879.8
   310.5  892.21   321.2  897.09     344  904.59   360.9  913.96   370.5  921.29
   404.8  953.69   411.3  957.74   431.3  965.47   435.1  968.29   437.3   971.7
#Mann= 3 ,-1,0
       0      .1       0  241.64    .045       0  273.09      .1       0
Bank Sta=241.64,273.09
XS Rating Curve= 0 ,0
Exp/Cntr(USF)=0,0
Exp/Cntr=0.3,0.1

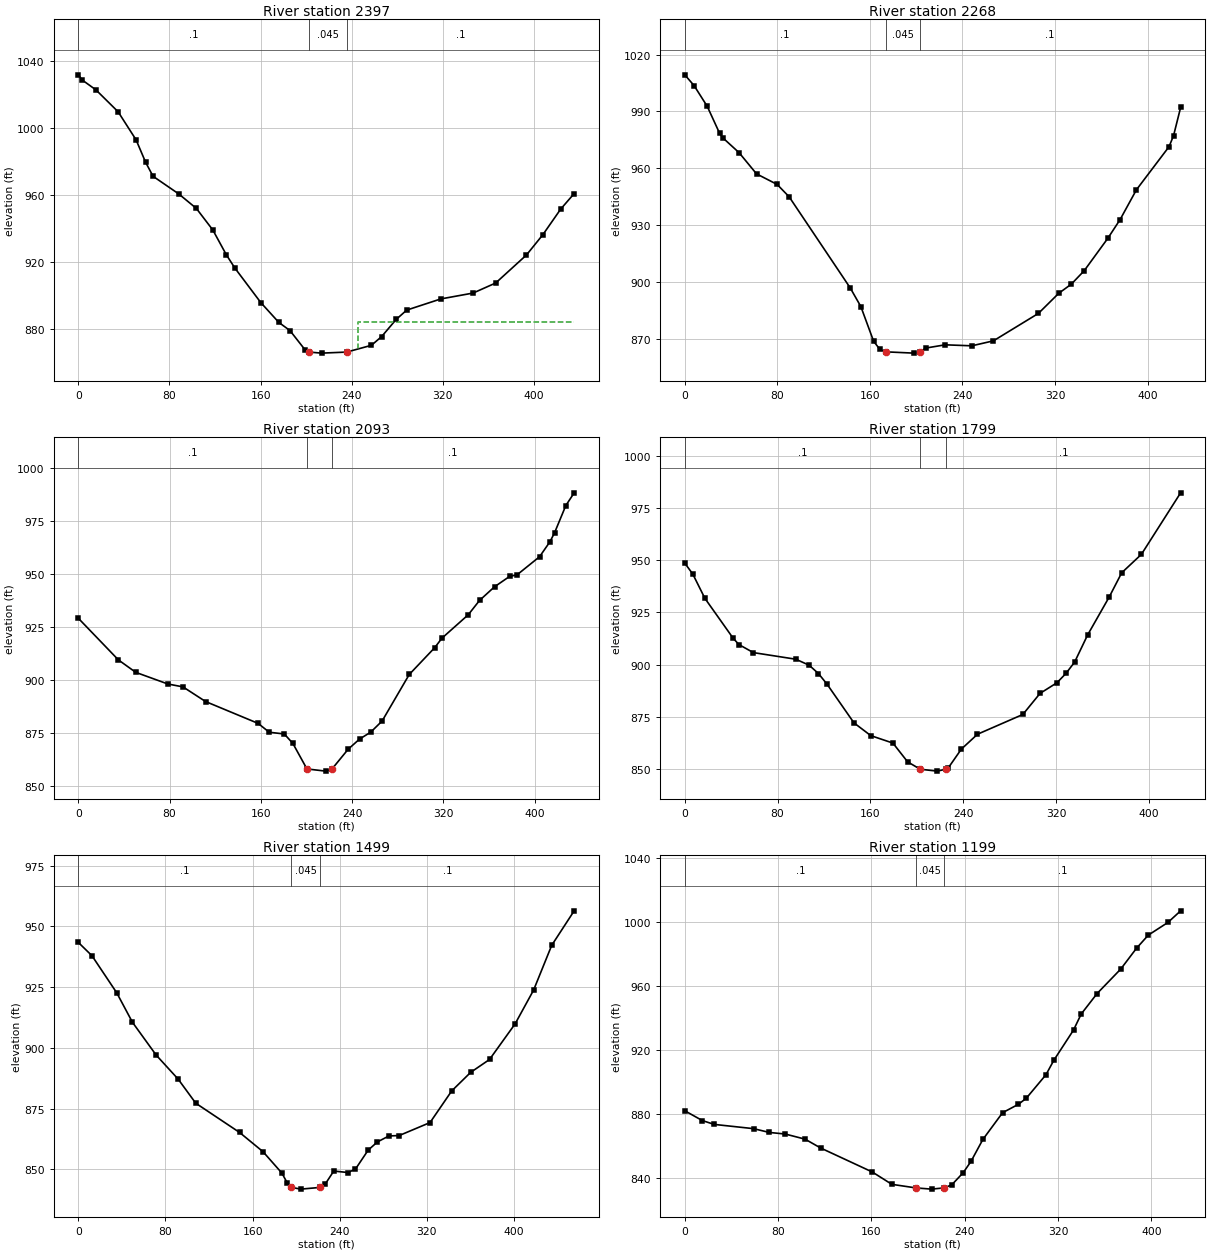
Type RM Length L Ch R = 1 ,2397    ,136.8,129.5,117.8
XS GIS Cut Line= 6
1620689.33165209457414.3003642561620732.11240642457334.672898844
1620783.05128093457279.6254367531620850.97010835 457206.22925809
1620899.54809517   457148.6188091620938.18548509 457062.33092384
#Sta/Elev= 30
       0 1031.99     3.4 1028.89    15.5 1022.95    34.9 1009.89    50.7  993.07
    59.1  979.59    65.6  971.25    88.2  960.67   103.6  952.02   118.1  939.08
     130  924.18   137.4  916.34   160.2  895.64     176  883.78   185.8  878.88
   199.2  867.23  202.56866.0079   213.6  865.38  235.61866.0093   257.3  870.06
   266.3  875.31   279.1  885.59   288.3  891.14   318.2  897.82   346.6  901.35
   366.4  907.36   393.4  924.12   407.8  936.26   423.5  951.62   435.3  960.91
#Mann= 3 ,-1,0
       0      .1       0  202.56    .045       0  235.61      .1       0
#XS Ineff= 2 , 0
                          245.85          883.94
Permanent Ineff=
       F       F
Bank Sta=202.56,235.61
XS Rating Curve= 0 ,0
Exp/Cntr(USF)=0,0
Exp/Cntr=0.3,0.1

Type RM Length L Ch R = 1 ,2268    ,176.2,174.7,169
XS GIS Cut Line= 4
 1620854.7312545457471.7660100261620918.87313526 457359.03432973
 1620933.8849597457255.1813980931621005.46179488457074.910509217
#Sta/Elev= 30
       0 1009.28     8.1 1003.53    19.4  992.63      30  978.51    33.1  975.88
    46.9  968.19      62  956.99    79.8  951.41    90.2  944.87     143  896.76
   152.2  886.89   163.2  868.62   168.7  864.25   173.5863.0188     198  862.33
  203.13863.0198   208.5  865.03   225.1  866.72   248.1  866.19   266.8  868.82
   305.7  883.32   323.3  893.95   334.1  898.74   345.3  905.88   365.7  922.99
   376.3  932.87   390.4  948.59   418.6  971.35   422.5  977.19   428.6  992.06
#Mann= 3 ,-1,0
       0      .1       0   173.5    .045       0  203.13      .1       0
Bank Sta=173.5,203.13
XS Rating Curve= 0 ,0
Exp/Cntr(USF)=0,0
Exp/Cntr=0.3,0.1

Type RM Length L Ch R = 1 ,2093    ,282.5,293.8,296.8
XS GIS Cut Line= 6
1621078.01099284457496.0042690931621094.15925451457406.313503593
 1621098.2183015 457330.062671841621088.61595851457229.331902176
1621092.44797184457152.4376990051621097.26981258457063.765304178
#Sta/Elev= 30
       0  929.18    35.1  909.54    50.3  903.67    78.4  898.18    91.7  896.81
   111.5   889.9   157.5   879.6   167.3  875.42   180.5  874.59     188  870.14
  200.32858.1053   216.7  857.07  222.33858.1067   236.5  867.43   246.4  872.17
   256.3  875.49   266.2   880.7     290  902.67   312.2  915.25   318.7  919.82
   341.7  930.84   351.6   937.6   364.7  944.02   377.9  948.91   384.5  949.68
   404.2  958.22   413.3  965.29   417.3  969.47   427.2  982.35   434.5  988.35
#Mann= 3 ,-1,0
       0      .1       0  200.32    .045       0  222.33      .1       0
Bank Sta=200.32,222.33
XS Rating Curve= 0 ,0
Exp/Cntr(USF)=0,0
Exp/Cntr=0.3,0.1

Type RM Length L Ch R = 1 ,1799    ,298.8,299.8,301.2
XS GIS Cut Line= 6
1621225.04449143457605.1549694241621271.10017359457530.756824255
1621310.57712875 457466.986938671621363.21252218457381.960205838
1621398.88502301457315.0892765821621441.74484542457236.954590335
#Sta/Elev= 30
       0  948.57     6.9  943.34    17.3  931.74    41.6  912.67    46.6   909.6
    59.1  905.73    95.7  902.56   107.2  899.69   115.2   895.7   122.7  890.54
   145.8  872.09   160.3  865.97   179.4  862.39   192.1  853.39  202.94849.8746
   217.5  848.96  225.16849.8751   227.1   850.5   238.4  859.51   252.3  866.63
   291.4   876.1   306.2  886.19   320.8  891.29   328.6  895.79     336  901.16
   347.2  914.15   365.9  932.43   376.6  943.95   393.6   952.8   427.4  982.26
#Mann= 3 ,-1,0
       0      .1       0  202.94    .045       0  225.16      .1       0
Bank Sta=202.94,225.16
XS Rating Curve= 0 ,0
Exp/Cntr(USF)=0,0
Exp/Cntr=0.3,0.1

Type RM Length L Ch R = 1 ,1499    ,306.8,300.2,294.7
XS GIS Cut Line= 6
1621373.43461458 457803.023668171621430.69270217 457736.85877426
1621479.77101609457680.1462892591621544.96543951457604.290797919
1621592.56934692457529.2164729981621649.26575585457442.277342424
#Sta/Elev= 30
       0  943.42    12.5  937.95    35.2  922.73    49.7  910.55    71.4   897.1
    91.6   887.2   107.8  877.27     148  865.25   169.6   857.3   186.9  848.51
   191.9  844.38  195.59842.6339   204.3  841.92  222.24842.6357   226.5  843.89
   234.5  849.36   247.5  848.75   254.4  850.15   266.1  857.97   274.6  861.35
   285.1  863.79   294.6  863.97   322.9  869.31   342.8  882.33   360.2  889.96
   377.5  895.26     401  909.92     418  923.85   434.6  942.23   455.2  956.42
#Mann= 3 ,-1,0
       0      .1       0  195.59    .045       0  222.24      .1       0
Bank Sta=195.59,222.24
XS Rating Curve= 0 ,0
Exp/Cntr(USF)=0,0
Exp/Cntr=0.3,0.1

Type RM Length L Ch R = 1 ,1199    ,306,300,291.4
XS GIS Cut Line= 6
1621743.60775876457895.9768943341621765.34065492457811.218861759
 1621783.9688985457738.5690726791621808.80677535457641.702796593
1621826.63974492457568.8489396721621846.75551835457483.676209763
#Sta/Elev= 30
       0  882.18      15  876.07    25.2  873.66    58.9  871.01    72.4  868.65
    86.2  867.63   103.1  864.44   116.6  858.86   160.7  843.93   177.5  836.21
  198.06833.9833   211.5  833.22   222.1833.9835   228.8  835.88   238.6  843.46
   245.3  850.53   255.5  864.27   272.4  880.98   285.9   886.2   292.7     890
   309.6  904.72   316.3  913.71   333.2  932.63   339.8  942.65   353.4  955.43
   373.7  970.75   387.2  983.74   397.3  991.94   414.1  999.84     425 1007.11
#Mann= 3 ,-1,0
       0      .1       0  198.06    .045       0   222.1      .1       0
Bank Sta=198.06,222.1
XS Rating Curve= 0 ,0
Exp/Cntr(USF)=0,0
Exp/Cntr=0.3,0.1