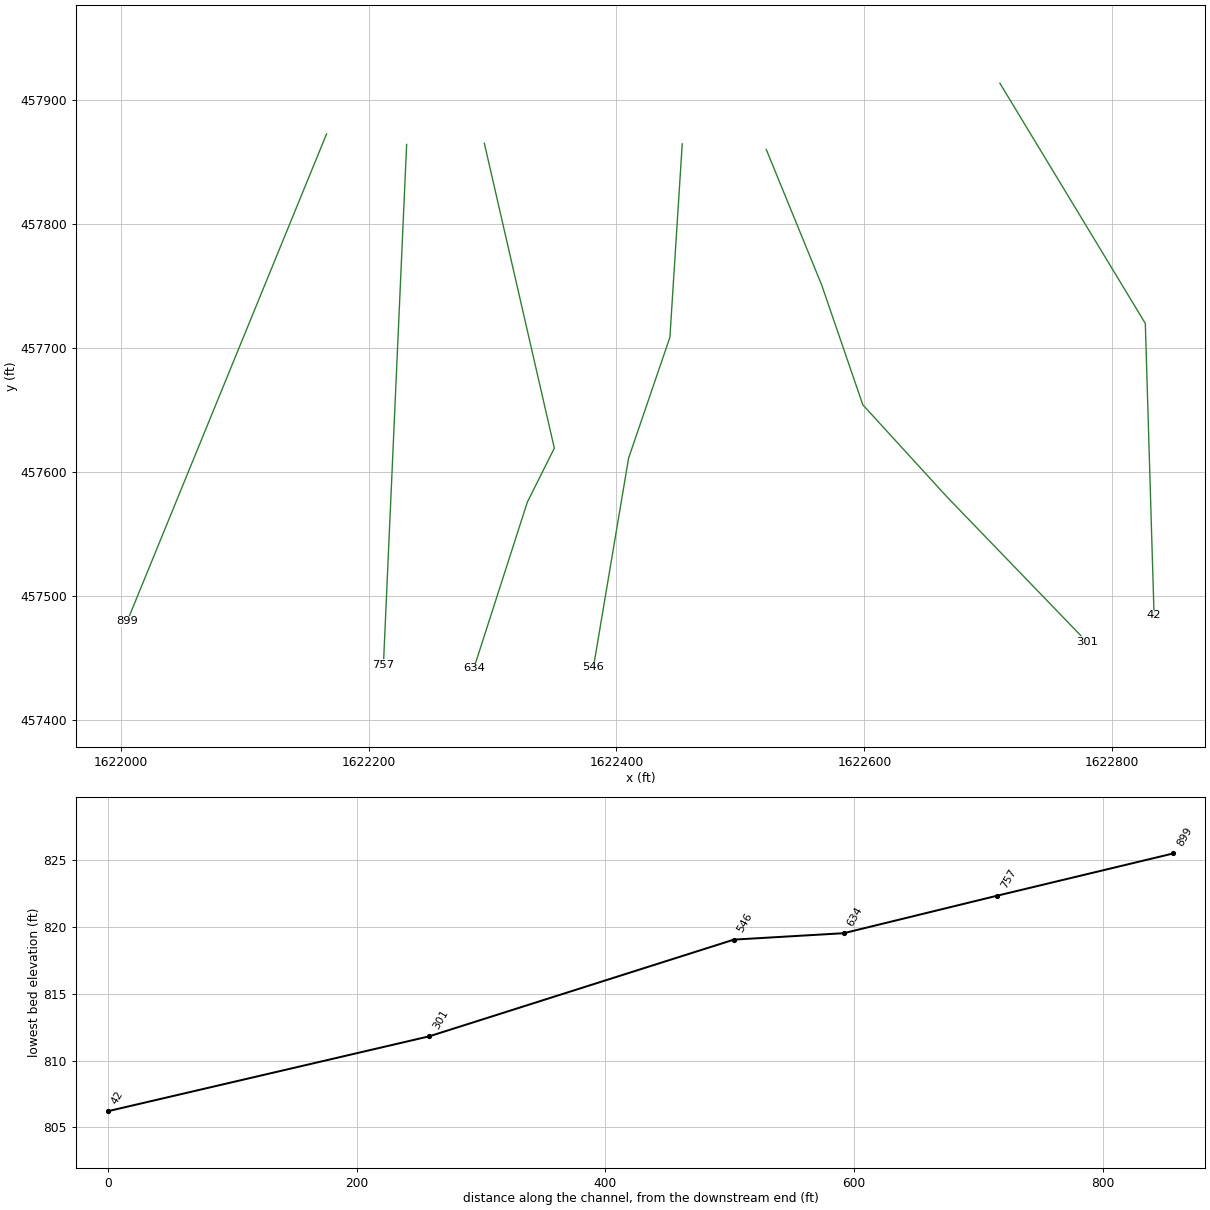
HEC-RAS study RockyFk.prj: RockyFk

--- RockyFk.g01 (geometry) --- (continued)

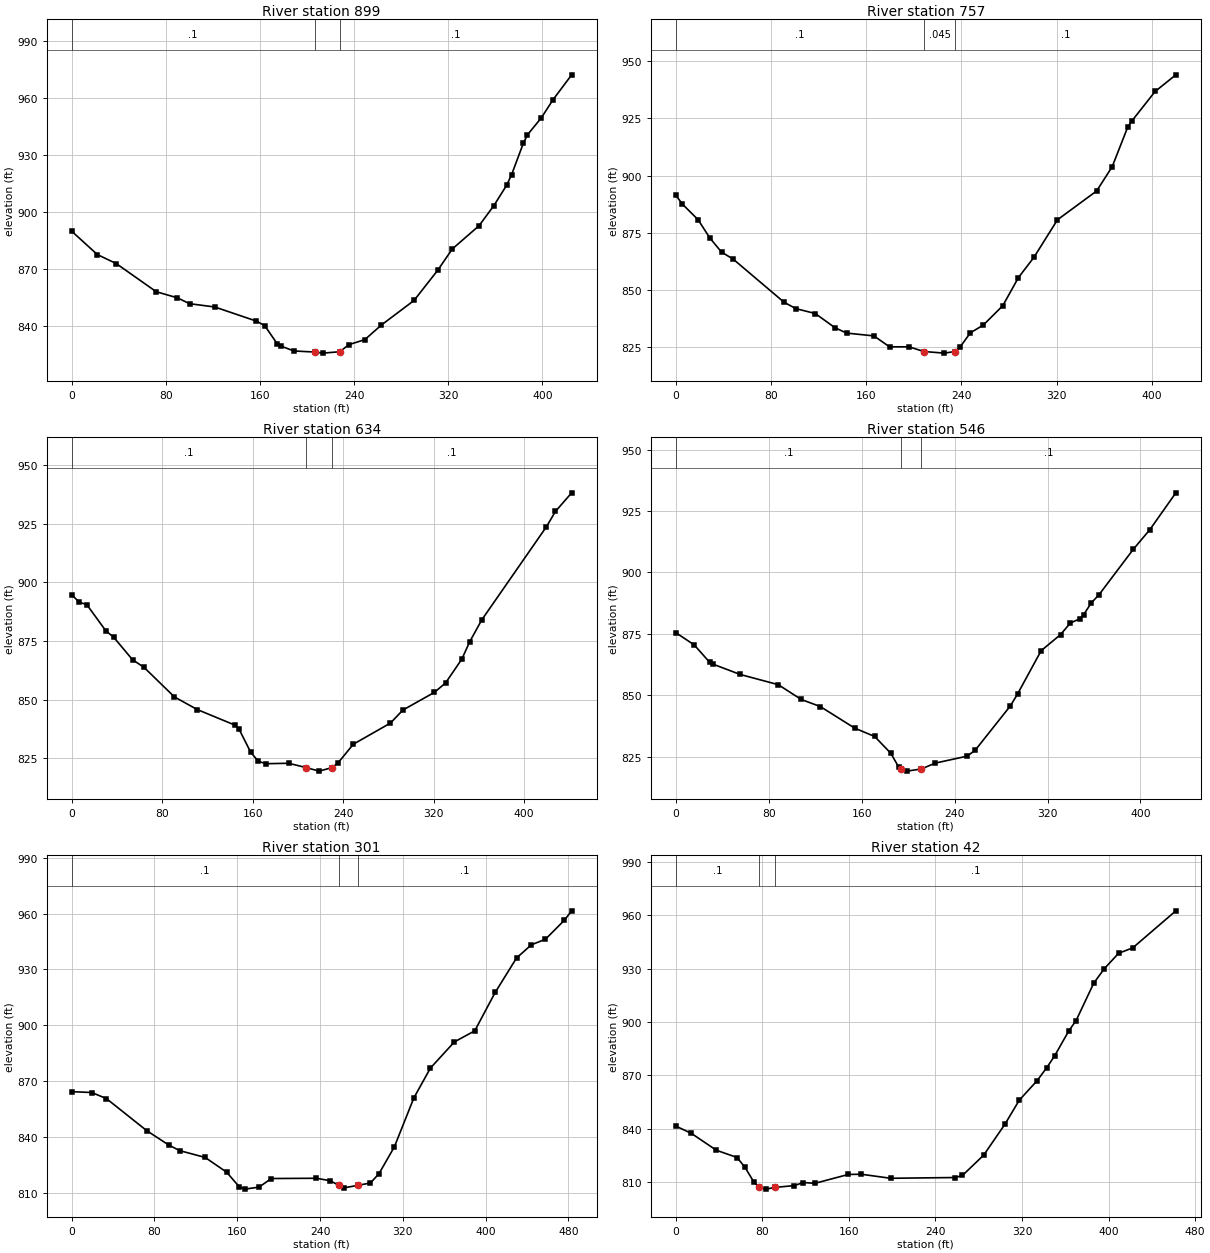
Type RM Length L Ch R = 1 ,899     ,136.8,141.5,144.9
XS GIS Cut Line= 6
1622166.16662492457872.5386210081622133.03611375457791.553218678
1622104.63951701457722.1370189191622066.77640375457629.582085922
1622038.37947892457560.1658861791622005.24896775457479.180483833
#Sta/Elev= 30
       0  889.85    21.8  877.52    37.9  872.75    71.9   857.9    89.7  854.71
   100.3  851.58   121.6  849.85     157   842.4   164.1     840   174.7  830.45
   178.3  829.13   188.9  826.64   206.6  826.07   213.7   825.5   227.9  826.24
   235.6  829.96   249.2  832.63   263.3  840.35     291  853.28   311.1  869.18
   323.6  880.49   346.3  892.74   358.9  903.36   369.7  914.05     374  919.75
   383.9  936.22   387.4  940.67   399.2  949.65   409.2  959.25     425  972.35
#Mann= 3 ,-1,0
       0      .1       0   206.6    .045       0   227.9      .1       0
Bank Sta=206.6,227.9
XS Rating Curve= 0 ,0
Exp/Cntr(USF)=0,0
Exp/Cntr=0.3,0.1

Type RM Length L Ch R = 1 ,757     ,118.9,123.5,125.6
XS GIS Cut Line= 2
1622230.74213561457863.992177382 1622212.0270599457444.123522221
#Sta/Elev= 30
       0  891.39     5.5  887.53    18.7  880.71    28.5  872.76    38.4  866.54
    48.2  863.46    90.9  844.63   100.8  841.82   117.2  839.67   133.6  833.51
   143.5  831.11   166.5  829.88   179.6   825.1     196   825.1  208.42823.0493
   225.6  822.34  234.79823.0489   238.7  824.85   247.6  831.23   258.4  834.59
   274.8  843.07     288  855.41   301.1  864.32   320.8  880.68   353.7  893.27
   366.8   903.9   379.9  921.29   383.2  923.83   402.9  936.82   420.3  944.09
#Mann= 3 ,-1,0
       0      .1       0  208.42    .045       0  234.79      .1       0
Bank Sta=208.42,234.79
XS Rating Curve= 0 ,0
Exp/Cntr(USF)=0,0
Exp/Cntr=0.3,0.1

Type RM Length L Ch R = 1 ,634     ,92.1,88.3,82
XS GIS Cut Line= 4
 1622293.4410057457864.9717380561622349.90357543457618.982410265
1622328.15340265457575.4820647141622284.94598872457441.246149906
#Sta/Elev= 30
       0  894.71     6.7  891.55    13.4  890.48    30.3  879.28      37  876.69
    53.8  867.01    63.9  863.79    90.8  851.17     111  845.78   144.7  839.07
   148.1  837.28   158.2  827.65   164.9  823.77   171.6  822.69   191.8  822.88
  207.09821.0565   218.8  819.53  230.28821.0577   235.6  823.12     249     831
   281.8  840.01   292.8  845.56   320.6  853.09   330.5   857.1     345  867.34
   351.8  874.62   362.6  884.05   419.7   923.7   427.7  930.24     442  938.15
#Mann= 3 ,-1,0
       0      .1       0  207.09    .045       0  230.28      .1       0
Bank Sta=207.09,230.28
XS Rating Curve= 0 ,0
Exp/Cntr(USF)=0,0
Exp/Cntr=0.3,0.1

Type RM Length L Ch R = 1 ,546     ,230.1,244.7,250.1
XS GIS Cut Line= 4
1622453.09985422457864.493922302 1622443.1416946457708.384538118
1622409.83817677457610.9483580121622381.44654555457442.212077118
#Sta/Elev= 30
       0  875.45    15.9  870.42    29.1  863.38    32.4  862.54    55.4  858.42
    88.2  854.26     108  848.23   124.4  845.35     154  836.56   171.2  833.16
   185.1  826.31     192  820.59  193.62819.9282   198.9  819.05  211.42819.9285
   223.2   822.3   250.9  825.16   257.9  827.66   287.9  845.54   294.2  850.45
   314.5  868.08   331.2  874.66   339.7  879.37   347.8  881.11   351.1  882.78
   357.7  887.56   364.4  890.93   393.8  909.36   408.1  917.39   430.5   932.4
#Mann= 3 ,-1,0
       0      .1       0  193.62    .045       0  211.42      .1       0
Bank Sta=193.62,211.42
XS Rating Curve= 0 ,0
Exp/Cntr(USF)=0,0
Exp/Cntr=0.3,0.1

Type RM Length L Ch R = 1 ,301     ,258.2,258.6,256.9
XS GIS Cut Line= 6
1622520.90410443457859.9641710821622565.59725651 457750.65172568
1622598.81077276 457653.930462421622666.48780276457579.895505503
1622718.56545451457525.9189074191622779.31500493457462.952826008
#Sta/Elev= 30
       0  864.24    19.4  863.78    33.5  860.54    72.5  843.29    93.8  835.54
   104.4  832.52     129  828.86   149.8  820.92     162  813.04   167.2  811.82
     181  812.88     193  817.52   236.6  817.66     250  816.32  258.19 813.845
   263.3  812.53   276.6  813.85   288.7  815.12     297  820.13   311.9   834.6
   330.7  860.89   346.7  876.92   369.9  891.01   389.5  896.93   409.3  917.61
   429.9   936.1   444.2   943.2   457.9  946.22   476.1   956.4   483.2  961.49
#Mann= 3 ,-1,0
       0      .1       0  258.19    .045       0   276.6      .1       0
Bank Sta=258.19,276.6
XS Rating Curve= 0 ,0
Exp/Cntr(USF)=0,0
Exp/Cntr=0.3,0.1

Type RM Length L Ch R = 1 ,42      ,,,
XS GIS Cut Line= 3
1622709.40399633457913.3898901631622826.72311009457719.615623615
1622833.78420871457484.054299848
#Sta/Elev= 30
       0  841.58    14.4  837.48    37.4  828.05    56.6  823.96      64  818.37
    71.9  810.41   76.88807.2047    83.4  806.21   91.93807.2033   109.4  808.18
   117.9  809.92   128.5  809.46   159.5  814.46   171.5  814.56   198.5   812.3
   258.3  812.72   264.9  813.87   284.6   825.3   304.3  842.72   317.4  856.07
   333.8  866.98   342.9  874.39   350.2  881.06   363.4  895.16     370  900.83
   386.3   921.8   396.2  930.03   409.3  938.57   422.4  941.63   462.2   962.4
#Mann= 3 ,-1,0
       0      .1       0   76.88    .045       0   91.93      .1       0
Bank Sta=76.88,91.93
XS Rating Curve= 0 ,0
Exp/Cntr(USF)=0,0
Exp/Cntr=0.3,0.1
LCMann Table=0

Chan Stop Cuts=-1
Use User Specified Reach Order=0
Composite Channel Slope=5